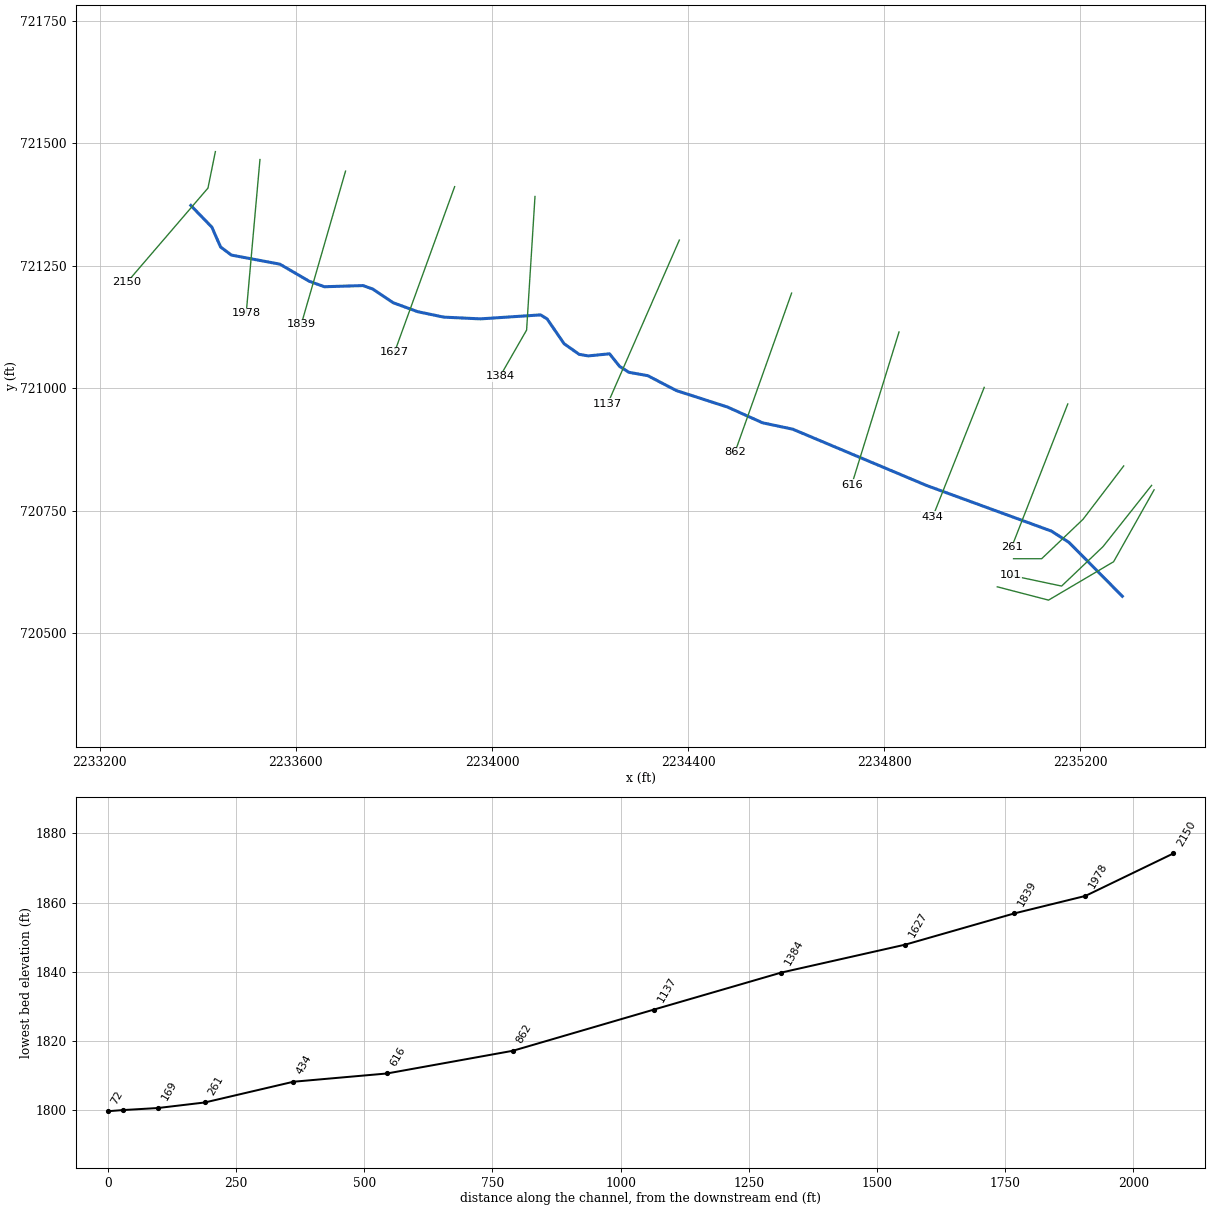
--- HOOPPOLERN.prj (project) ---

Proj Title=HOOPPOLERN
Current Plan=p01
Default Exp/Contr=0,0
English Units
Geom File=g01
Flow File=f01
Plan File=p01
BEGIN DESCRIPTION:
---------- MODELED AS PART OF WVEMD CTP PROGRAM, 2023----------
Stream Name: Hooppole Run
Flood Zone:  AFH
Upshur County, WV
HEC-RAS Version: RAS 6.3
Vertical Datum: NAVD88
Projection: NAD 1983 StatePlane West Virginia S FIPS 4702 (US Feet)
Terrain: 1-meter LIDAR (FEMA Region III 3DEP collected 2016-2018)
Land Use: 2019 NLCD
Hydrologic Method:
WV 2010 Regional Regression Equations
Additional Model Notes:
None
END DESCRIPTION:
DSS Export Rating Curves= 0
DSS Export Rating Curve Sorted= 0
DSS Export Volume Flow Curves= 0
DXF OffsetX= 0
DXF OffsetY= 0
DXF ScaleX= 0
DXF ScaleY= 0

--- HOOPPOLERN.p01 (plan) ---

Plan Title=Floodplain
Program Version=4.00
Geom File=g01
Flow File=f01
K Sum by GR=0
Std Step Tol=0.01
Critical Tol=0.01
Num of Std Step Trials=20
Max Error Tol=0.3
Flow Tol Ratio=0.001
Split Flow NTrial=30
Split Flow Tol=0.02
Split Flow Ratio=0.02
Log Output Level=0
Friction Slope Method=1
Unsteady Friction Slope Method=2
Unsteady Bridges Friction Slope Method=1
Global Log Level=0
CheckData=False
Run HTab=0
Run UNet=0
Run PostProcess=0
UNET Theta=0
UNET Theta Warmup=0
UNET ZTol=0
UNET ZSATol=0
UNET MxIter=0
UNET MaxInSteps=0
UNET DtIC=0
UNET DtMin=0
UNET MaxCRTS=0
UNET WFStab=0
UNET SFStab=0
UNET WFX=0
UNET SFX=0
UNET DSS MLevel=0
UNET DZMax Abort=0
UNET Convert EG Bridges=0
UNET Use Existing IB Tables=0
UNET Froude Limit=0
UNET Froude Power=0
Write IC File=0
Echo Input=False
Echo Output=False
Write Detailed=0

--- HOOPPOLERN.f01 (steady flow) ---

Flow Title=Flows
Program Version=6.31
Number of Profiles= 1
Profile Names=01pct
River Rch & RM=HOOPPOLERN,Main            ,2150
     319
Boundary for River Rch & Prof#=HOOPPOLERN,Main            , 1
Up Type= 0
Dn Type= 3
Dn Slope=0.01066
DSS Import GetInterval= 0
DSS Import GetPeak= 0
DSS Import FillOption= 0

--- HOOPPOLERN.g01 (geometry) ---

Geom Title=Geometry
Program Version=6.31

River Reach=HOOPPOLERN      ,Main
Reach XY= 30
     2233385.675      721372.975     2233428.657      721328.505
     2233446.399      721288.127     2233468.433      721271.673
     2233567.332      721253.158     2233626.882      721218.446
     2233658.046      721207.143     2233736.683      721209.518
     2233756.515      721202.564     2233798.237      721174.577
     2233848.259      721156.291     2233901.457      721145.188
     2233976.317      721141.611     2234099.024      721149.738
     2234112.331      721141.411     2234146.871      721090.989
     2234177.633      721069.269     2234196.205      721066.092
     2234239.531      721070.414     2234260.106      721044.716
      2234279.05       721032.64      2234317.51      721025.801
      2234375.83       720995.41     2234480.252      720961.728
     2234551.735      720929.621     2234613.232      720916.658
     2234886.175       720801.82     2235140.804       720708.76
     2235176.546      720685.752     2235285.345      720575.951

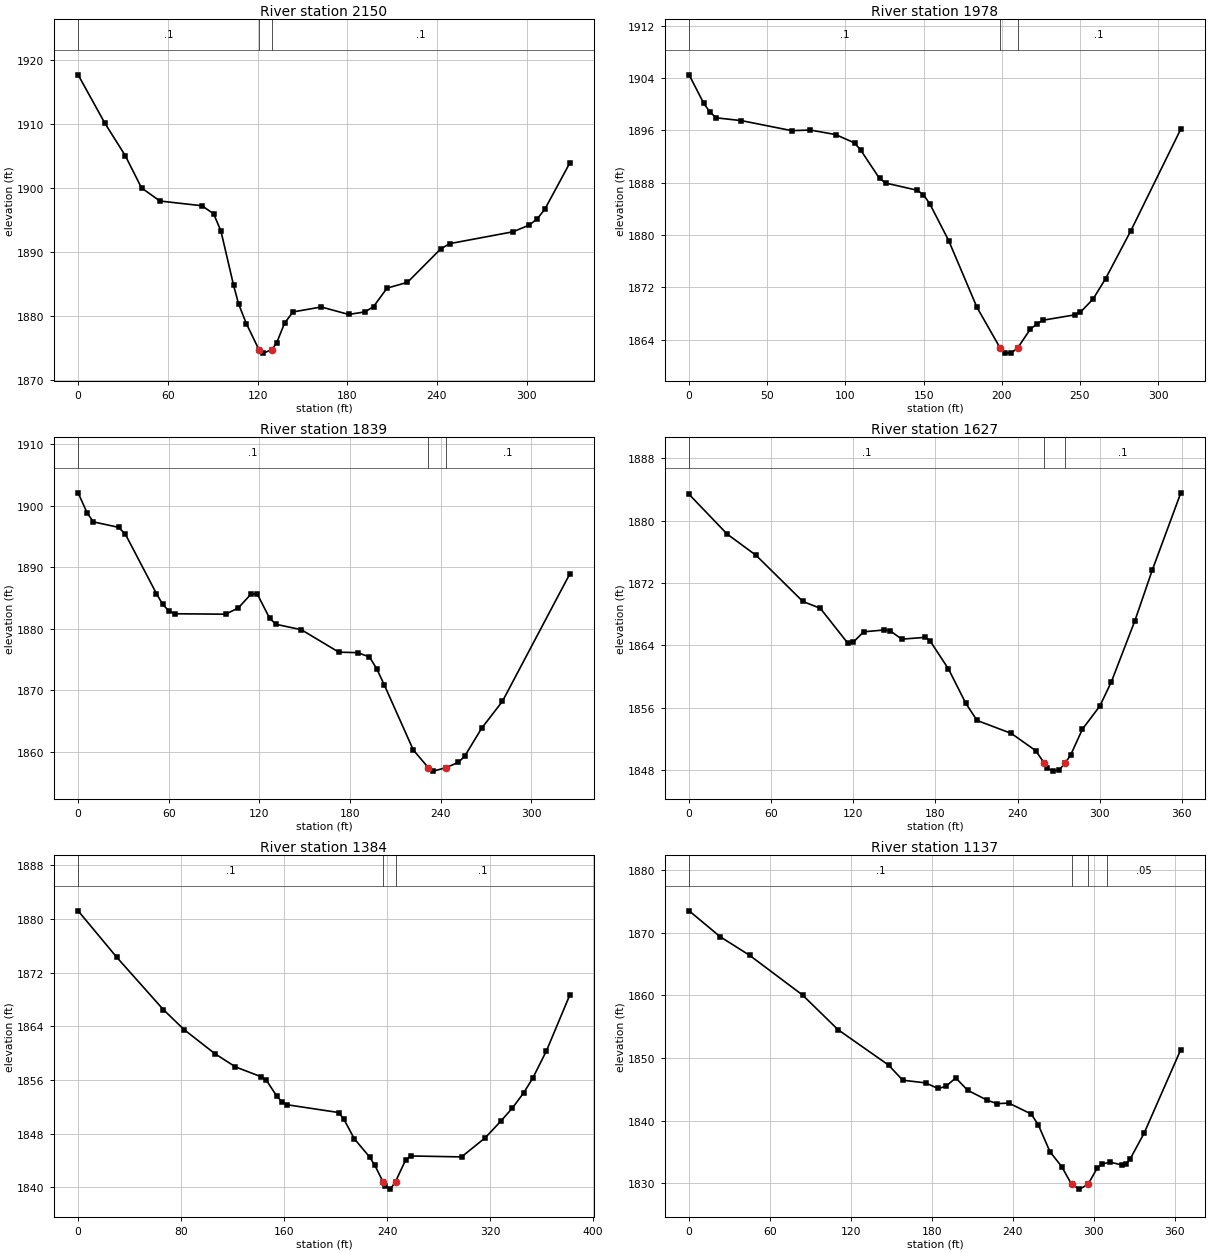
Type RM Length L Ch R = 1 ,2150    ,171.7,171.7,171.7
XS GIS Cut Line= 3
2233435.72194263721482.754157631  2233420.644844721408.373804375
2233255.80189894 721216.39208178
#Sta/Elev= 30
       0  1917.7    17.9 1910.14    31.5 1905.09    42.4 1900.04    54.7 1897.99
    82.8 1897.25    90.6    1896    95.5 1893.32     104 1884.81   107.3 1881.93
   112.5 1878.85  120.931874.779   123.9 1874.23   129.6 1874.78   132.8 1875.84
   138.1 1878.92   143.7 1880.66   162.6 1881.44     181 1880.27     192 1880.68
   197.6  1881.5   206.6 1884.38   220.3 1885.29   242.4 1890.48   248.5 1891.33
     291 1893.19   301.5 1894.21   306.8 1895.14   312.1 1896.68   328.9 1903.94
#Mann= 3 ,-1,0
       0      .1       0  120.93    .045       0   129.6      .1       0
Bank Sta=120.93,129.6
XS Rating Curve= 0 ,0
Exp/Cntr(USF)=0,0
Exp/Cntr=0.3,0.1

Type RM Length L Ch R = 1 ,1978    ,140.1,138.5,136
XS GIS Cut Line= 2
2233526.64780879721466.5188730952233498.63757495721153.252948537
#Sta/Elev= 30
       0 1904.51     9.4 1900.13    13.4 1898.79    17.4 1897.93    33.5  1897.5
    65.6 1895.97    77.6 1896.06    93.7 1895.37   105.8 1894.09   109.8 1892.98
   121.8 1888.65   125.8 1887.95   145.9 1886.85   149.9 1886.17     154 1884.74
     166 1879.16   184.1 1868.94   198.9 1862.73   202.1 1861.98     206 1861.93
  210.141862.728   218.2 1865.58   222.2 1866.35   226.2 1866.96   246.8 1867.79
   250.3  1868.2   258.4 1870.21   266.4 1873.34   282.5 1880.64   314.5 1896.22
#Mann= 3 ,-1,0
       0      .1       0   198.9    .045       0  210.14      .1       0
Bank Sta=198.9,210.14
XS Rating Curve= 0 ,0
Exp/Cntr(USF)=0,0
Exp/Cntr=0.3,0.1

Type RM Length L Ch R = 1 ,1839    ,212.7,212.4,210.6
XS GIS Cut Line= 2
2233701.18130771721442.897080097 2233610.8091785721130.258362841
#Sta/Elev= 30
       0  1902.1       6 1898.81    10.1 1897.38    26.8 1896.49    31.3 1895.36
    51.8 1885.74    55.9    1884    60.3 1882.84    64.2 1882.45    97.6 1882.38
   105.9 1883.38   114.2 1885.58   118.4 1885.74   126.7 1881.73   130.9 1880.74
   147.7 1879.86   172.5 1876.21     185 1876.13   192.8 1875.43   197.5 1873.55
   202.5 1870.95   221.8 1860.32  231.761857.434     235 1856.88   243.3 1857.43
   251.6  1858.3   255.8  1859.3   267.1 1863.87   280.8 1868.23   325.4 1888.94
#Mann= 3 ,-1,0
       0      .1       0  231.76    .045       0   243.3      .1       0
Bank Sta=231.76,243.3
XS Rating Curve= 0 ,0
Exp/Cntr(USF)=0,0
Exp/Cntr=0.3,0.1

Type RM Length L Ch R = 1 ,1627    ,239.2,242.5,246.5
XS GIS Cut Line= 2
 2233923.6975055721411.2805159462233801.07043662721073.553506565
#Sta/Elev= 30
       0 1883.36    27.8 1878.27      49 1875.53    83.1 1869.63    95.9 1868.74
   115.8 1864.31   119.9 1864.39   127.5 1865.73   142.7 1865.97   146.9 1865.86
   155.4 1864.79   172.5 1865.02   176.1 1864.56   189.5 1860.97   202.2 1856.55
   210.4 1854.36   235.4  1852.7   253.3 1850.48  259.611848.858   261.8 1848.21
   266.1 1847.86   270.3    1848   274.6 1848.85   278.8 1849.93   287.4 1853.25
   300.1  1856.2   308.6 1859.34   325.7 1867.14   338.4 1873.63   359.3 1883.56
#Mann= 3 ,-1,0
       0      .1       0  259.61    .045       0   274.6      .1       0
Bank Sta=259.61,274.6
XS Rating Curve= 0 ,0
Exp/Cntr(USF)=0,0
Exp/Cntr=0.3,0.1

Type RM Length L Ch R = 1 ,1384    ,250.5,247.6,242.9
XS GIS Cut Line= 3
2234087.53531065721391.1777177682234070.44793219721118.784802464
2234016.17037712 721024.30165103
#Sta/Elev= 30
       0 1881.21    30.1 1874.27    66.1 1866.51    82.2 1863.53   106.2 1859.93
   122.2 1857.96   142.3 1856.48   146.3 1855.94   154.3  1853.6   158.3 1852.76
   162.3 1852.32   202.4 1851.16   206.4 1850.16   214.4 1847.28   226.4 1844.53
   230.5 1843.28  236.741840.848   238.5  1840.2   242.5 1839.75   246.5 1840.87
   254.5 1844.15   258.5 1844.69   297.8 1844.55   316.3 1847.42   328.5 1849.92
   337.3 1851.84   346.1 1854.11   353.2 1856.32   363.7 1860.34   381.9 1868.69
#Mann= 3 ,-1,0
       0      .1       0  236.74    .045       0   246.5      .1       0
Bank Sta=236.74,246.5
XS Rating Curve= 0 ,0
Exp/Cntr(USF)=0,0
Exp/Cntr=0.3,0.1

Type RM Length L Ch R = 1 ,1137    ,274.2,275.1,275.6
XS GIS Cut Line= 2
2234381.92962173721302.2786769392234235.62592389720968.348862769
#Sta/Elev= 30
       0 1873.51      23 1869.38    44.9  1866.4    84.1 1860.07   110.4 1854.54
   147.9 1848.88   158.4 1846.47   175.3 1846.04   184.6 1845.15   190.4 1845.48
   197.7 1846.84   206.5 1844.87   220.8  1843.3   228.3 1842.72     237 1842.82
   253.6 1841.08   258.9 1839.35   267.6 1835.04   276.3 1832.67  283.661829.819
   289.4 1829.08  295.751829.827   302.5  1832.4   305.8 1833.03   311.9  1833.4
     321 1832.93   324.1 1833.09   327.1 1833.92   337.5 1838.07   364.6 1851.37
#Mann= 4 ,-1,0
       0      .1       0  283.66    .045       0  295.75      .1       0
     310     .05       0
Bank Sta=283.66,295.75
XS Rating Curve= 0 ,0
Exp/Cntr(USF)=0,0
Exp/Cntr=0.3,0.1

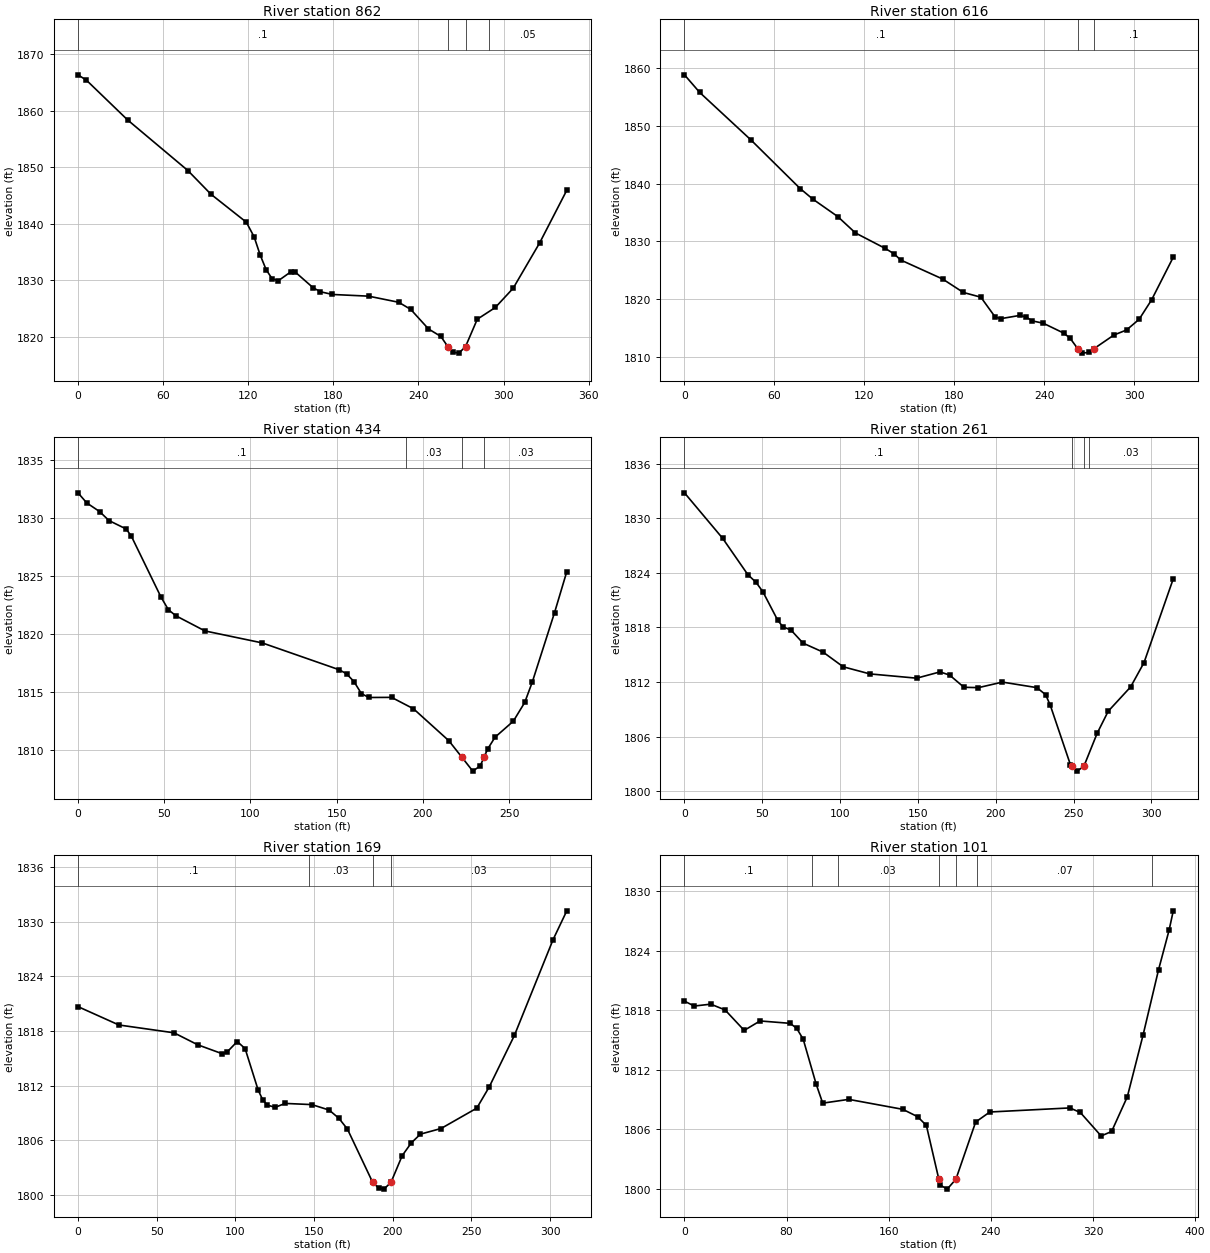
Type RM Length L Ch R = 1 ,862     ,245,245.6,245.8
XS GIS Cut Line= 2
2234610.85609585721194.1675380442234495.26500633720869.507347478
#Sta/Elev= 30
       0 1866.31       6 1865.35      35 1858.34    77.5  1849.4    93.7 1845.23
   118.7 1840.28   124.2 1837.68   128.4 1834.52   132.7 1831.87   136.9 1830.29
   141.2 1829.94     150 1831.51   153.2 1831.47   165.7 1828.72   170.9    1828
   179.4 1827.52   204.9 1827.22   226.1 1826.14   234.6 1824.88   247.1 1821.43
   255.8 1820.11   260.9 1818.25   264.3 1817.33   268.5 1817.16  273.191818.302
   281.5 1823.15   294.2 1825.22   306.8 1828.62   325.4  1836.6   344.6 1845.93
#Mann= 4 ,-1,0
       0      .1       0   260.9    .045       0  273.19      .1       0
     290     .05       0
Bank Sta=260.9,273.19
XS Rating Curve= 0 ,0
Exp/Cntr(USF)=0,0
Exp/Cntr=0.3,0.1

Type RM Length L Ch R = 1 ,616     ,183.2,182.5,181.6
XS GIS Cut Line= 2
2234829.93798978721114.9324555432234733.42249785720803.325295865
#Sta/Elev= 30
       0 1858.85    10.2 1855.79    44.4 1847.55    77.2 1839.13    85.6 1837.31
   102.3 1834.27   114.1 1831.43   133.9 1828.76     140 1827.79   144.2 1826.75
   172.3 1823.44   186.1 1821.11   197.8 1820.29   207.4 1816.83   211.2 1816.57
   223.8 1817.13     228 1816.85   232.1 1816.18   239.4 1815.78   253.1 1814.06
   257.3 1813.19  262.561811.322   265.6 1810.59   269.8 1810.72     273 1811.31
   286.6 1813.73     295  1814.6   303.4 1816.45   311.7 1819.81   326.2 1827.23
#Mann= 3 ,-1,0
       0      .1       0  262.56    .045       0     273      .1       0
Bank Sta=262.56,273
XS Rating Curve= 0 ,0
Exp/Cntr(USF)=0,0
Exp/Cntr=0.3,0.1

Type RM Length L Ch R = 1 ,434     ,172.3,172.5,172.7
XS GIS Cut Line= 2
2235003.66587527721001.8714507042234898.87762688720738.522036994
#Sta/Elev= 30
       0 1832.16     5.1 1831.29    12.5 1830.55      18 1829.77    27.9 1829.05
    30.9 1828.44    48.1 1823.19    52.4  1822.1    56.7 1821.58    73.6 1820.27
   106.8 1819.24   151.4 1816.93   155.7 1816.58     160 1815.91   164.3 1814.88
   168.6 1814.54   181.8 1814.55   194.5 1813.57     215 1810.82  222.55  1809.4
   228.9  1808.2   233.2 1808.65  235.421809.399   237.5  1810.1   241.8 1811.12
   252.4  1812.5     259 1814.11   263.4 1815.87   276.3 1821.85   283.4 1825.38
#Mann= 4 ,-1,0
       0      .1       0     190     .03       0  222.55    .045       0
  235.42     .03       0
Bank Sta=222.55,235.42
XS Rating Curve= 0 ,0
Exp/Cntr(USF)=0,0
Exp/Cntr=0.3,0.1

Type RM Length L Ch R = 1 ,261     ,96.1,91.7,86.9
XS GIS Cut Line= 2
2235174.04605197720968.1089528322235059.46010236 720675.61323935
#Sta/Elev= 30
       0 1832.78    24.6 1827.77    40.7  1823.8    46.1 1822.93    50.4 1821.91
      60 1818.76    63.3 1818.06    68.5  1817.7    76.2 1816.27    89.1 1815.28
     102 1813.67   119.1 1812.89   149.2 1812.42   164.2 1813.11   170.4 1812.76
   179.6 1811.42   188.9 1811.38   204.3 1811.99   226.5 1811.38   232.1  1810.6
   235.1 1809.43     248 1802.92   249.1 1802.74   252.3 1802.21  256.641802.734
   265.2 1806.37   272.3 1808.79   286.7 1811.46   295.3 1814.13   314.1 1823.34
#Mann= 4 ,-1,0
       0      .1       0   249.1    .045       0  256.64      .1       0
     260     .03       0
Bank Sta=249.1,256.64
XS Rating Curve= 0 ,0
Exp/Cntr(USF)=0,0
Exp/Cntr=0.3,0.1

Type RM Length L Ch R = 1 ,169     ,68.7,68.8,68.8
XS GIS Cut Line= 4
2235288.10486318720841.6693211232235205.20538915720732.906214156
 2235120.7736368720652.495021446  2235063.480662720652.495021446
#Sta/Elev= 30
       0 1820.68      26 1818.66      61  1817.8    76.1 1816.48    91.6  1815.5
    94.5 1815.64   101.2 1816.84   106.2 1816.06   114.5 1811.49   117.3 1810.46
   120.2 1809.85   125.3  1809.6   131.6 1810.03   148.6  1809.9   159.6  1809.3
   165.8 1808.39   171.2 1807.21  187.24 1801.35     191 1800.73   194.4  1800.6
   198.9 1801.35     206 1804.28   211.8 1805.69   217.6 1806.65   230.7 1807.27
   253.4 1809.51   261.3 1811.84   277.3 1817.51   301.9 1828.06   310.6 1831.22
#Mann= 4 ,-1,0
       0      .1       0  146.75     .03       0  187.24    .045       0
   198.9     .03       0
Bank Sta=187.24,198.9
XS Rating Curve= 0 ,0
Exp/Cntr(USF)=0,0
Exp/Cntr=0.3,0.1

Type RM Length L Ch R = 1 ,101     ,29.6,29,29.6
XS GIS Cut Line= 4
2235344.98103898720802.0617612332235245.91355546720677.120949214
2235161.48180311720596.7097565042235056.94725259720618.822834499
#Sta/Elev= 30
       0 1818.91     7.7 1818.42    20.6 1818.61    31.8 1818.03    46.8 1815.97
    59.2 1816.92    82.8 1816.68    87.9 1816.18      93 1815.09   103.2 1810.55
   108.3 1808.65   128.7 1809.03     171 1808.03   182.6 1807.29   189.5 1806.41
  199.27 1800.99   200.5  1800.4   205.8    1800  212.61 1800.99   228.1 1806.75
   239.2 1807.76   301.9 1808.17   310.1 1807.71   326.4 1805.35   334.6  1805.8
   346.9 1809.29   359.2 1815.48   371.4 1822.09   379.6 1826.04   382.9    1828
#Mann= 7 ,-1,0
       0      .1       0     100     .06       0     120     .03       0
  199.27    .045       0  212.61     .03       0  229.45     .07       0
  366.05     .08       0
Bank Sta=199.27,212.61
XS Rating Curve= 0 ,0
Exp/Cntr(USF)=0,0
Exp/Cntr=0.3,0.1

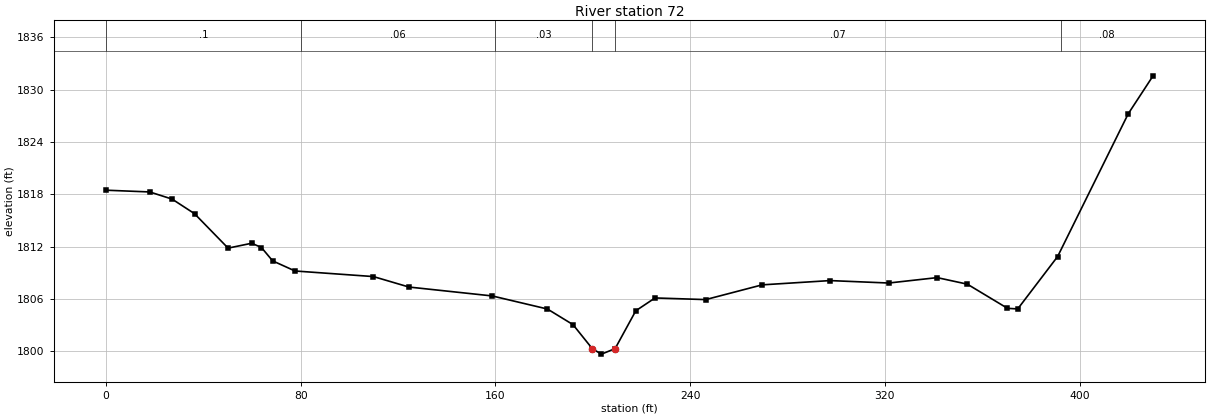
Type RM Length L Ch R = 1 ,72      ,,,
XS GIS Cut Line= 4
2235350.04317608720792.8899612392235267.54525434720646.368894622
2235134.84559553720568.0632691012235030.31104501720595.202046641
#Sta/Elev= 30
       0 1818.46      18 1818.26    27.2 1817.44    36.4 1815.77    50.2 1811.82
    59.9 1812.38    63.9 1811.89    68.5 1810.36    77.7  1809.2   109.9 1808.56
   124.5 1807.36   158.7 1806.34   181.4 1804.84   191.9 1803.05   199.9 1800.27
   203.6 1799.67   209.2  1800.3   217.7 1804.64   225.6 1806.11   246.4 1805.92
   269.6 1807.61   297.5  1808.1   321.6 1807.82   341.5 1808.44   353.9 1807.69
   370.4 1804.92   374.6 1804.85     391 1810.86     420 1827.22   430.2 1831.57
#Mann= 6 ,-1,0
       0      .1       0      80     .06       0     160     .03       0
   199.9    .045       0   209.2     .07       0  392.23     .08       0
Bank Sta=199.9,209.2
XS Rating Curve= 0 ,0
Exp/Cntr(USF)=0,0
Exp/Cntr=0.3,0.1
LCMann Table=0

Chan Stop Cuts=-1
Use User Specified Reach Order=0
Composite Channel Slope=5